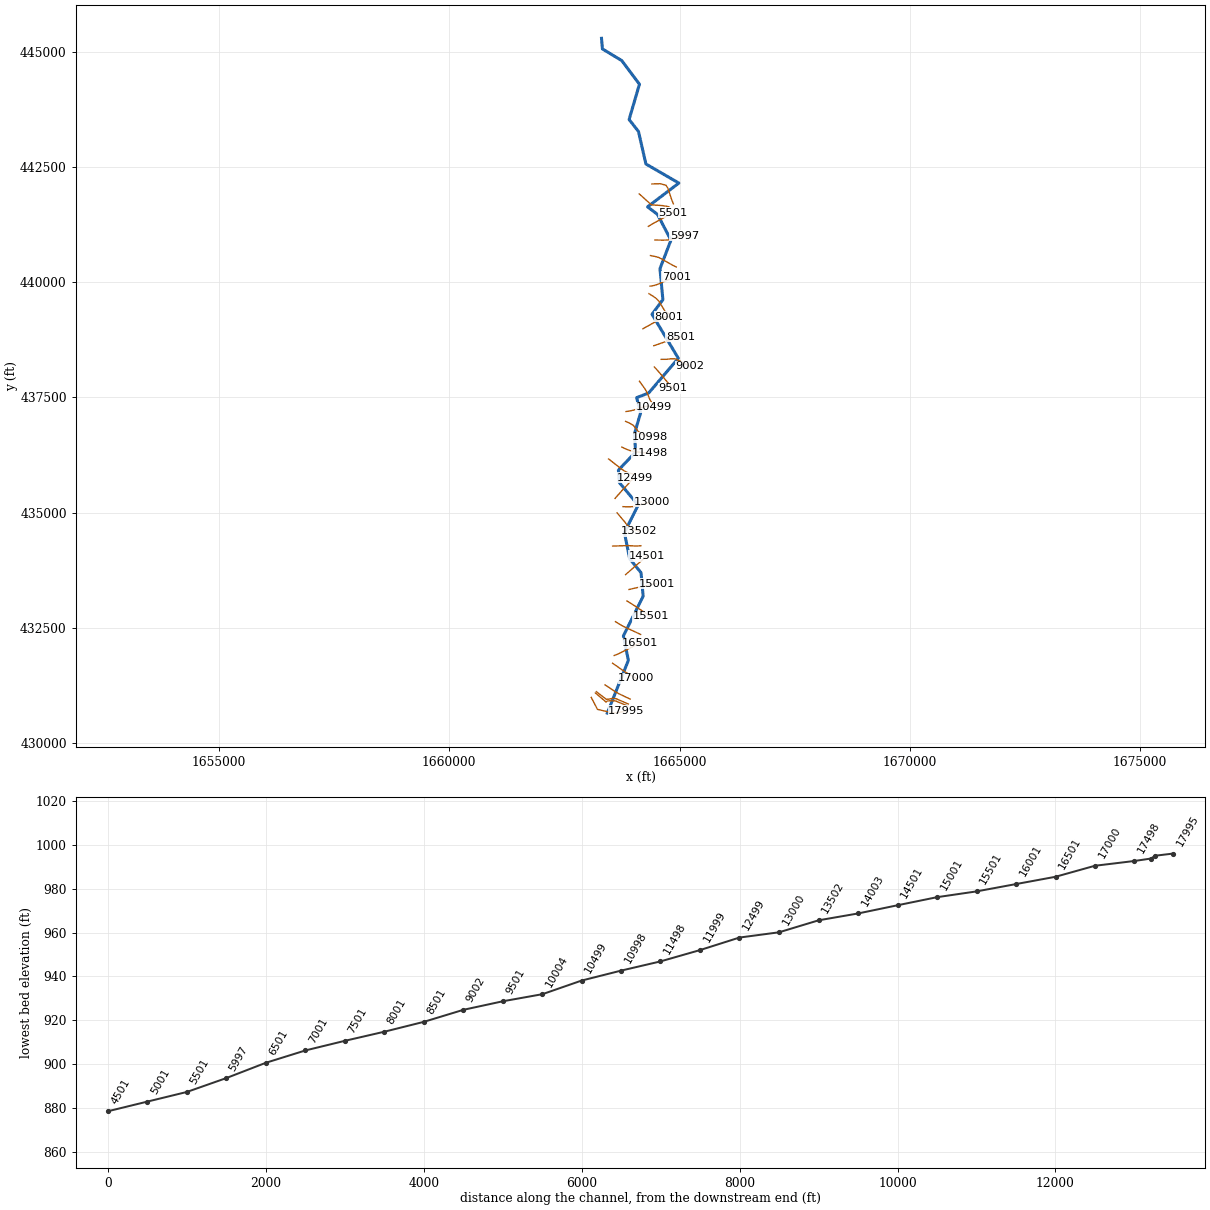
--- ROCKYRN.prj (project) ---

Proj Title=ROCKYRN
Current Plan=p01
Default Exp/Contr=0,0
English Units
Geom File=g01
Flow File=f01
Plan File=p01
BEGIN DESCRIPTION:
---------- MODELED AS PART OF WVEMD CTP PROGRAM, 2023----------
Stream Name: Rocky Run
Flood Zone:  AFH
Wetzel County, WV
HEC-RAS Version: RAS 6.3
Vertical Datum: NAVD88
Projection: NAD 1983 StatePlane West Virginia S FIPS 4702 (US Feet)
Terrain: 1-meter West Virginia FEMA R3 South Central (collected 2018-2020)
Land Use: 2019 NLCD
Hydrologic Method:
WV SIR2010-5033 regression equations
Additional Model Notes:
None
END DESCRIPTION:
DSS Export Rating Curves= 0
DSS Export Rating Curve Sorted= 0
DSS Export Volume Flow Curves= 0
DXF OffsetX= 0
DXF OffsetY= 0
DXF ScaleX= 0
DXF ScaleY= 0

--- ROCKYRN.p01 (plan) ---

Plan Title=Floodplain
Program Version=6.30
Short Identifier=Floodplain
Geom File=g01
Flow File=f01
Subcritical Flow
K Sum by GR= 0
Std Step Tol= 0.01
Critical Tol= 0.01
Num of Std Step Trials= 20
Max Error Tol= 0.3
Flow Tol Ratio= 0.001
Split Flow NTrial= 30
Split Flow Tol= 0.02
Split Flow Ratio= 0.02
Log Output Level= 0
Friction Slope Method= 1
Unsteady Friction Slope Method= 2
Unsteady Bridges Friction Slope Method= 1
Parabolic Critical Depth
Global Vel Dist= 0 , 0 , 0
Global Log Level= 0
CheckData=True
Encroach Param=-1 ,0,0, 0
Mapping Interval=1HOUR
Computation Time Step Use Courant=        0
Computation Time Step Use Time Series=    0
Computation Time Step Count To Double=0
Computation Time Step Max Doubling=0
Computation Time Step Max Halving=0
Computation Time Step Residence Courant=0
Run HTab= 0
Run UNet= 0
Run Sediment= 0
Run PostProcess= 0
Run WQNet= 0
Run RASMapper= 0
UNET Theta= 0
UNET Theta Warmup= 0
UNET ZTol= 0
UNET ZSATol= 0
UNET MxIter= 0
UNET Max Iter WO Improvement= 0
UNET MaxInSteps= 0
UNET DtIC= 0
UNET DtMin= 0
UNET MaxCRTS= 0
UNET WFStab= 0
UNET SFStab= 0
UNET WFX= 1
UNET SFX= 1
UNET Gravity=32.17405
UNET 1D Methodology=Finite Difference
UNET DSS MLevel= 1
UNET Pardiso=0
UNET DZMax Abort= 0
UNET Use Existing IB Tables= 0
UNET Froude Reduction=False
UNET Froude Limit= 0
UNET Froude Power= 0
UNET D1 Cores= 0
UNET WindReference=Eulerian
UNET WindDragFormulation=Hsu (1988)
UNET D2 Coriolis=0
UNET D2 Cores= 0
UNET D2 Theta= 1
UNET D2 Theta Warmup= 1
UNET D2 Z Tol= 0.01
UNET D2 Volume Tol= 0.01
UNET D2 Max Iterations= 20
UNET D2 Equation= 0
UNET D2 RampUpFraction=0.1
UNET D2 TimeSlices= 1
UNET D2 Turbulence Formulation=Non-Conservative (original)
UNET D2 Eddy Viscosity=0.3
UNET D2 Transverse Eddy Viscosity=0.1
UNET D2 Smagorinsky Mixing=0
UNET D2 BCVolumeCheck=0
UNET D2 Cores=0
UNET D2 SolverType=PARDISO (Direct)
UNET D2 Minimum Iterations= 3
UNET D2 Maximum Iterations= 30
UNET D2 Restart Number= 10
UNET D2 Relaxation Coeff=1.3
UNET D2 SOR Precondition Iterations= 10
UNET D2 ILUT Maximum Fill= 8
UNET D2 ILUT Tolerance=1E-08
UNET D2 Convergence Tolerance=0.00001
UNET D1D2 MaxIter= 0
UNET D1D2 ZTol=0.01
UNET D1D2 QTol=0.1
UNET D1D2 MinQTol=1
Write IC File= 0
Write IC File at Fixed DateTime=0
Write IC File at Sim End=0
Echo Input=False
Echo Parameters=False
Echo Output=False
Write Detailed= 0
HDF Write Warmup=0
HDF Write Time Slices=0
HDF Flush=0
HDF Compression= 1
HDF Chunk Size= 1
HDF Spatial Parts= 1
HDF Use Max Rows=0
HDF Fixed Rows= 1
Calibration Method= 0
Calibration Iterations= 20
Calibration Max Change=0.05
Calibration Tolerance=0.2
Calibration Maximum=1.5
Calibration Minimum=0.5
Calibration Optimization Method= 1
WQ AD Non Conservative
WQ ULTIMATE=-1
WQ Max Comp Step=1HOUR
WQ Output Interval=15MIN
WQ Output Selected Increments= 0
WQ Output face flow=0
WQ Output face velocity=0
WQ Output face area=0
WQ Output face dispersion=0
WQ Output cell volume=0
WQ Output cell surface area=0
WQ Output cell continuity=0
WQ Output cumulative cell continuity=0
WQ Output face conc=0
WQ Output face dconc_dx=0
WQ Output face courant=0
WQ Output face peclet=0
WQ Output face adv mass=0
WQ Output face disp mass=0
WQ Output cell mass=0
WQ Output cell source sink temp=0
WQ Output nsm pathways=0
WQ Output nsm derived pathways=0
WQ Create Restart=0
WQ Fixed Restart=0
WQ System Summary=0
WQ Write To DSS=0
Sorting and Armoring Iterations= 10
XS Update Threshold= 0.02
Bed Roughness Predictor= 0
Hydraulics Update Threshold= 0.02
Energy Slope Method= 1
Volume Change Method= 1
Sediment Retention Method= 0
Sediment TS Multiplier= 1
Warm Up Method= 0
XS Weighting Method= 0
Number of US Weighted Cross Sections= 1
Number of DS Weighted Cross Sections= 1
Upstream XS Weight=0
Main XS Weight=1
Downstream XS Weight=0
Number of DS XS's Weighted with US Boundary= 1
Upstream Boundary Weight= 1
Weight of XSs Associated with US Boundary= 0
Number of US XS's Weighted with DS Boundary= 1
Downstream Boundary Weight= 0.5
Weight of XSs Associated with DS Boundary= 0.5
Percentile Method= 0
Sediment Output Level= 3
Mass or Volume Output= 0
Output Increment Type= 1
Profile and TS Output Increment= 1
Transport Output Increment 1
XS Output Flag= 0
XS Output Increment= 10
Read HDF5 Sediment Hotstart= 0
Sediment Hotstart Type= 0
Write Gradation File= 0
Read Gradation Hotstart= 0
Write HDF5 File= 1
Write Binary Output= 1
Write DSS Sediment File= 0
DSS Sediment Output Type= 1
SV Curve= 0
Specific Gage Flag= 0
Subcell Erosion Methods= 0
Subcell Deposition Methods= 0
Advection Scheme= 1
Matrix Solver= 0
Implicit Weighting Factor= 1
Maximum Outer Loop Convergence Iterations= 5
Convergence Maximum Absolute= 0.001
Convergence RMSE= 0.0001
Grain Fractions Max Abs Error= 0.001
Max Subgrid Regions= 1
Max Subgrid Length Scale= 3.402823E+38
Initial Layer Thickness= 3.402823E+38
Min Layer Thickness= 3.402823E+38
Max Layer Thickness= 3.402823E+38
Number of Layers= 5

--- ROCKYRN.f01 (steady flow) ---

Flow Title=Flow
Program Version=4.00
Number of Profiles=1
Profile Names=F01pct
River Rch & RM=ROCKYRN,Main,17995
    2080
River Rch & RM=ROCKYRN,Main,5001
    3060
Boundary for River Rch & Prof#=ROCKYRN,Main      ,1
Up Type=0
Dn Type=3
Dn Slope=0.014889

--- ROCKYRN.g01 (geometry) ---

Geom Title=Geometry
Program Version=6.30

River Reach=ROCKYRN         ,Main
Reach XY= 30
1663431.49404526430647.068344601     1663889.576      431792.904
     1663781.079      432322.852     1664210.756      433184.164
     1664164.538      433694.137     1663918.952      433995.733
     1663803.405       434564.851664101.86963782 435160.31102861
      1663692.95      435652.163     1663673.366      435919.684
     1664047.816      436315.284     1664020.398      436701.876
     1664155.137      437166.021     1664068.184      437492.685
1664331.21276365437595.097236354     1664973.756      438348.514
     1664403.073      439303.047     1664638.866      439620.311
     1664575.806      440292.832     1664813.557      440911.692
     1664521.361        441471.8     1664305.935      441634.349
     1664985.507      442150.588     1664269.901      442564.989
      1664109.31       443270.02     1663905.635      443529.706
      1664130.07      444295.448     1663745.436      444809.337
     1663326.335      445061.581     1663306.707      445291.966

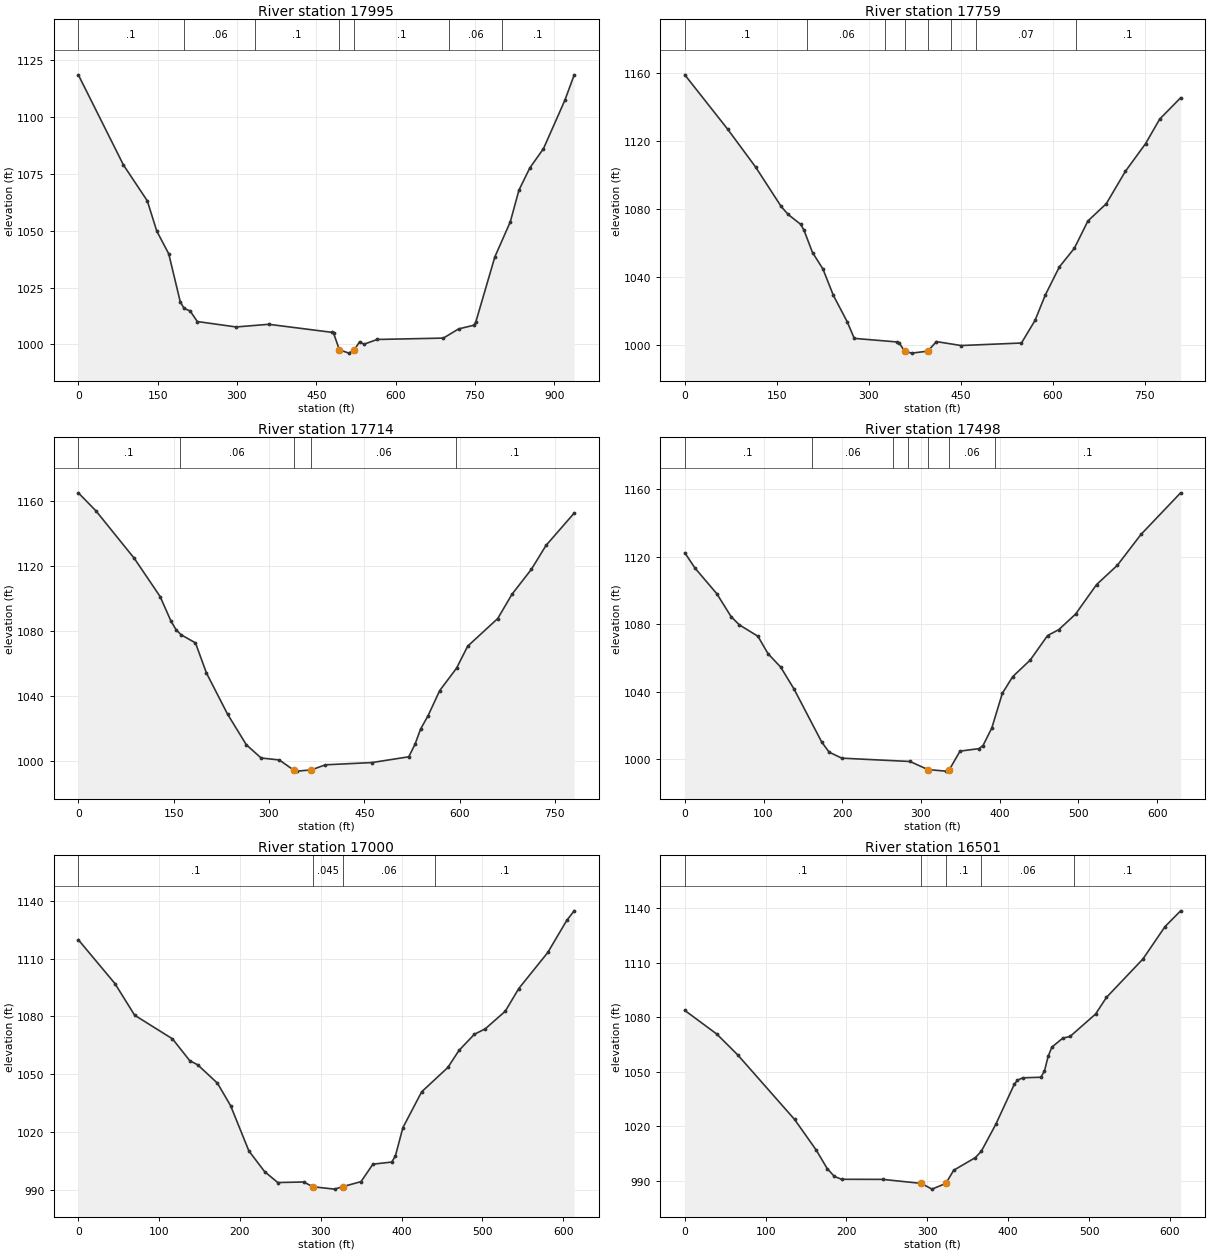
Type RM Length L Ch R = 1 ,17995   ,230.9,236.3,241.5
BEGIN DESCRIPTION:
Structure XS 4
END DESCRIPTION:
XS GIS Cut Line= 6
1663084.02974235430988.2860449211663219.11109367430727.906859641
1663304.43441384430708.5020428051663548.59567092430654.787255217
1663659.44366111430653.0637656841663849.21704817430702.061532839
#Sta/Elev= 30
       0 1118.38    85.3 1078.81   130.4 1063.07   148.4 1049.75     171 1039.79
   192.7 1018.78     200 1015.84   211.5  1014.7     225 1010.06   298.5 1007.68
     360 1008.85   478.8 1005.34   482.9 1004.83  493.69997.6691   511.6  996.19
   521.5   997.5     532 1001.21   540.2 1000.09   565.2 1002.19   690.4 1002.79
   719.2 1006.83   748.4 1008.46   751.7 1009.86   787.8  1038.5   816.8 1053.76
   833.3 1067.76   853.9 1077.53   879.7 1085.98     920 1107.15   937.7 1118.31
#Mann= 7 ,-1,0
       0      .1       0     200     .06       0  333.33      .1       0
  493.69    .045       0   521.5      .1       0  700.84     .06       0
   801.7      .1       0
Bank Sta=493.69,521.5
XS Rating Curve= 0 ,0
Exp/Cntr(USF)=0,0
Exp/Cntr=0.3,0.1

Type RM Length L Ch R = 1 ,17759   ,50,45.1,45.3
BEGIN DESCRIPTION:
Structure XS 3
END DESCRIPTION:
XS GIS Cut Line= 6
1663172.04071556431086.0415754291663405.99021005  430886.7842113
1663430.89738056430909.0227564041663448.68821665430912.580923621
1663607.02665779430913.4704654251663875.66828264430801.388198102
#Sta/Elev= 30
       0 1158.89    70.2 1126.78   115.7 1104.53   157.2 1081.43   168.5 1076.76
   189.2 1070.89   194.5 1067.39   208.3 1054.36   225.3 1044.66   242.3 1029.16
     265 1013.53   276.4 1003.84     346 1001.74   350.1 1000.92   358.8   996.2
   370.3  995.16  396.12996.3188   410.4 1001.94   450.5  999.63   549.1 1001.11
   571.2 1014.39   588.1 1029.44   610.9 1045.87   635.4 1056.87   657.5 1072.94
   687.4 1083.05   718.7 1102.17   751.6 1118.45   774.5 1132.83   808.7 1145.37
#Mann= 8 ,-1,0
       0      .1       0     200     .06       0   327.3      .1       0
   358.8    .045       0  396.12      .1       0  434.17     .06       0
  474.24     .07       0  637.62      .1       0
Bank Sta=358.8,396.12
XS Rating Curve= 0 ,0
Exp/Cntr(USF)=0,0
Exp/Cntr=0.3,0.1

Type RM Length L Ch R = 1 ,17714   ,216,215.4,204
BEGIN DESCRIPTION:
Structure XS 2
END DESCRIPTION:
XS GIS Cut Line= 6
1663194.27926066431113.6173713581663413.10654448 430944.60442857
1663508.28751753430957.0580138281663556.32277495430968.622057282
1663618.59070124430961.505722849 1663889.9009515430844.086204701
#Sta/Elev= 30
       0 1164.76    27.6 1153.75    88.2 1124.46   128.7  1101.1   145.7  1086.1
   153.9 1080.64   161.8 1077.63   184.3 1072.65   201.7 1054.09   234.8 1028.92
   264.4 1010.09   287.7 1001.97   316.2 1000.77   338.7  994.62   344.3  993.91
  366.73994.6826   388.9  997.79   462.1  999.17     520 1002.71   529.9 1010.45
   538.6 1019.71   550.5 1028.03   568.7 1043.36   595.3 1057.16   612.7 1070.61
     660 1087.59   682.5 1102.51     713 1117.82     736 1132.47   780.3 1152.29
#Mann= 5 ,-1,0
       0      .1       0     160     .06       0   338.7    .045       0
  366.73     .06       0  594.68      .1       0
Bank Sta=338.7,366.73
XS Rating Curve= 0 ,0
Exp/Cntr(USF)=0,0
Exp/Cntr=0.3,0.1

Type RM Length L Ch R = 1 ,17498   ,499.7,498.4,494.5
BEGIN DESCRIPTION:
Structure XS 1
END DESCRIPTION:
XS GIS Cut Line= 6
1663381.85158184431260.2496540841663467.06794684431205.732046589
1663544.44935375431152.6990161691663608.87901492 431108.12823917
1663697.28730267431060.8698035031663928.73762718430950.930062756
#Sta/Elev= 30
       0 1122.39      13 1113.27    40.7 1098.06    58.8  1084.5    69.2 1079.62
    92.9 1072.83   105.7 1062.49   121.8 1054.52   138.7 1041.54     174 1009.96
   183.3 1004.05   199.4 1000.47   286.1  998.49   308.7   993.7   331.4  992.77
   335.9  993.54   349.6 1004.64   373.6 1006.12   378.8 1007.97     390 1018.43
   403.3 1038.91   416.5 1048.85   438.7 1058.67   460.8 1073.24     475 1076.75
   496.3 1085.94     523 1103.49   549.4 1114.95   579.4 1133.25   629.8 1157.97
#Mann= 7 ,-1,0
       0      .1       0  161.16     .06       0  264.97      .1       0
  283.32     .06       0   308.7    .045       0   335.9     .06       0
  393.56      .1       0
Bank Sta=308.7,335.9
XS Rating Curve= 0 ,0
Exp/Cntr(USF)=0,0
Exp/Cntr=0.3,0.1

Type RM Length L Ch R = 1 ,17000   ,482.4,498.5,516.8
XS GIS Cut Line= 6
1663546.90735409 431729.543663011663757.21041118431583.130570009
1663841.01503359431528.4866504221663905.91943134431490.448668763
1663981.89040801431446.4300560061664063.42174101431399.371423095
#Sta/Elev= 30
       0 1119.75    45.3 1097.05    69.7 1080.65   116.5 1068.42   137.9  1057.1
   147.7 1054.97   172.1 1045.48   188.4 1033.81     211 1010.41   230.5  999.65
   246.8     994   278.8  994.29   290.3  991.82     317  990.59   326.9  991.83
   349.8  994.48   364.5 1003.52   387.8 1004.61   392.3 1007.77   401.6 1022.44
   424.8 1040.99   457.2 1053.59     471 1062.43   490.1 1070.81   503.4 1073.57
   528.2  1082.7     545 1094.49   580.9 1113.17   604.3 1129.74   613.5 1134.72
#Mann= 4 ,-1,0
       0      .1       0   290.3    .045       0   326.9     .06       0
  441.53      .1       0
Bank Sta=290.3,326.9
XS Rating Curve= 0 ,0
Exp/Cntr(USF)=0,0
Exp/Cntr=0.3,0.1

Type RM Length L Ch R = 1 ,16501   ,511.2,500,489.8
XS GIS Cut Line= 6
1663583.13858084431897.6706233321663670.79030843431931.959596753
 1663905.5778966432049.3520785121663972.33038776432083.552469417
1664049.84007525432124.1891991791664136.02527034432162.011302009
#Sta/Elev= 30
       0 1083.77    39.7 1070.73    65.5 1059.31   135.8 1023.85   162.7 1006.94
   176.1  996.87     185  992.54     194  990.97   244.6  990.92   292.3  988.72
   305.8  985.56  322.88988.7115   332.6  995.92   359.5 1002.91   366.8  1006.4
   384.6 1021.11   407.5 1043.11   411.4 1045.39   417.9 1046.73   440.4 1047.04
   444.9 1050.46   449.4  1058.5     454 1063.57   467.5 1068.52   476.6 1069.46
   508.2 1081.82   521.6 1090.94   566.7 1112.03     594 1129.83   613.3 1138.49
#Mann= 5 ,-1,0
       0      .1       0   292.3    .045       0  322.88      .1       0
  366.62     .06       0  481.62      .1       0
Bank Sta=292.3,322.88
XS Rating Curve= 0 ,0
Exp/Cntr(USF)=0,0
Exp/Cntr=0.3,0.1

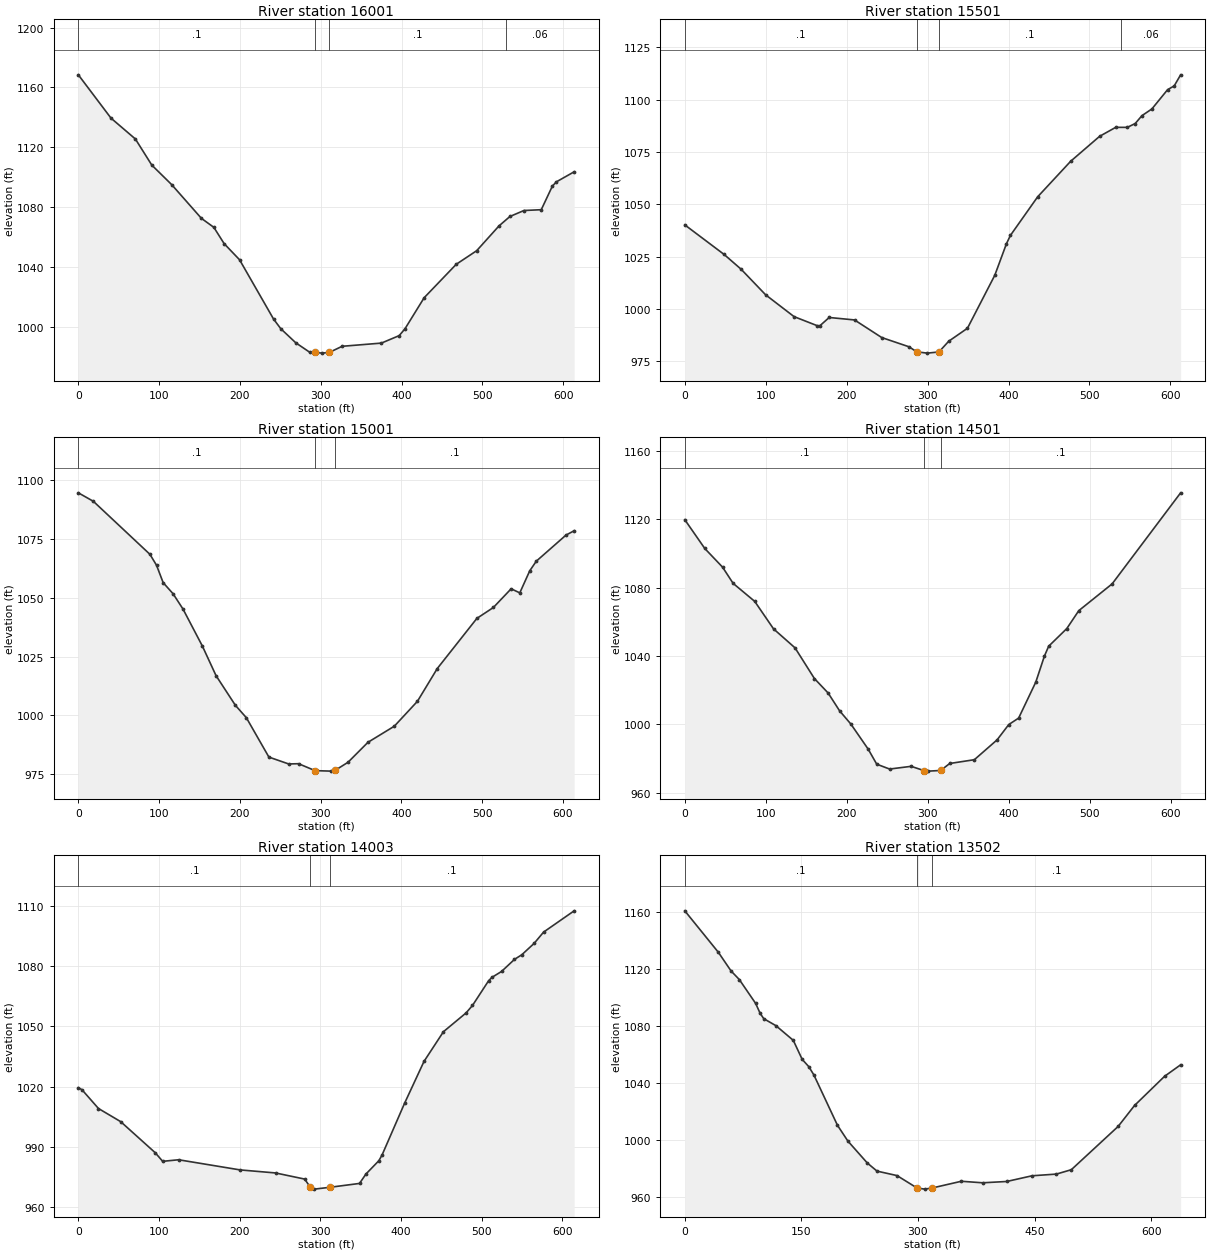
Type RM Length L Ch R = 1 ,16001   ,501.6,500,498.7
XS GIS Cut Line= 6
1663609.91969526  432631.73674051663689.78600533432581.538678169
1663765.65921317432537.2113390121663833.31524584432504.832138672
1663924.01617992432462.7203462571664156.43763109432354.811769426
#Sta/Elev= 30
       0  1168.4    40.4 1139.44    70.6 1125.47    90.9 1108.02   115.6  1094.9
   152.3 1072.38   167.7 1066.36   180.4 1055.47   199.5 1044.68   241.5 1005.08
   250.5  998.56   269.1  989.12   286.6  982.71   292.7  982.73   301.7  982.23
   310.7  982.74   326.4   986.8     375  988.94     397  993.94   404.1  998.45
   427.9 1019.29   467.6 1041.66   492.9 1050.75   520.5 1067.33     534 1073.63
   551.4 1077.64   572.8 1078.18   586.6 1094.02   591.6 1096.84   613.5 1103.53
#Mann= 4 ,-1,0
       0      .1       0   292.7    .045       0   310.7      .1       0
  529.71     .06       0
Bank Sta=292.7,310.7
XS Rating Curve= 0 ,0
Exp/Cntr(USF)=0,0
Exp/Cntr=0.3,0.1

Type RM Length L Ch R = 1 ,15501   ,486,500,506.9
XS GIS Cut Line= 6
1663858.72333151433081.0088078381663938.59390667433031.780559838
1664012.51305017432984.9013885111664075.01948684 432943.45101209
1664158.01439959432887.6670029161664370.68949917432744.721422672
#Sta/Elev= 30
       0 1040.13    48.6    1026    69.5 1018.98    99.9 1006.72     135  996.31
   163.9  991.94   167.1  992.02   178.4   995.9   209.7  994.73   243.3  986.32
     277  981.91   286.6  979.49   299.6  978.88     314  979.44   326.1  984.57
   349.2  990.75     383 1016.06   397.4 1031.13   402.3  1035.1     436 1053.55
   476.7 1070.49   512.5 1082.42   532.4 1086.71   546.8  1086.7   556.5 1088.54
   564.8 1092.29   577.1  1095.5   596.5  1104.7   604.7 1106.52   612.6 1111.79
#Mann= 4 ,-1,0
       0      .1       0   286.6    .045       0     314      .1       0
  538.86     .06       0
Bank Sta=286.6,314
XS Rating Curve= 0 ,0
Exp/Cntr(USF)=0,0
Exp/Cntr=0.3,0.1

Type RM Length L Ch R = 1 ,15001   ,493.9,500,504.5
XS GIS Cut Line= 6
1663902.02541025433329.5634288341663993.90416351433351.729723096
1664079.77472667433370.7874277531664153.40089175433385.648946583
1664251.25568293433406.2509395031664502.00879034433459.042500585
#Sta/Elev= 30
       0 1094.71    18.6  1091.1    88.6 1068.54    96.8 1063.89     105 1056.48
   117.3 1051.74   129.6 1045.22   153.6 1029.45   170.5 1016.87   194.4 1004.27
     208  998.98   235.9  982.22   260.4  979.29   272.6   979.4   293.1  976.45
     313  976.24   317.6  976.51   333.9  980.02   358.5   988.5   391.2  995.37
   419.8 1005.97   444.3 1019.89   493.4 1041.27   513.8  1045.9   535.8 1053.86
   546.5 1052.12   558.8  1061.5   566.9  1065.6   603.7 1076.72   613.8 1078.57
#Mann= 3 ,-1,0
       0      .1       0   293.1    .045       0   317.6      .1       0
Bank Sta=293.1,317.6
XS Rating Curve= 0 ,0
Exp/Cntr(USF)=0,0
Exp/Cntr=0.3,0.1

Type RM Length L Ch R = 1 ,14501   ,508.5,498.7,492.8
XS GIS Cut Line= 6
1663829.44550292433653.370524004 1663900.2078286433714.943235502
1663966.09877293433772.5175954251664022.57766259433821.868218511
1664097.92003159433887.6216959211664290.88060367434056.228642166
#Sta/Elev= 30
       0 1119.87    24.7    1103    46.7 1092.04    59.7 1082.57    86.4    1072
   109.6 1055.92   136.2 1044.77   160.1 1026.81   177.1  1018.3   191.2  1007.9
   205.2  1000.1   226.5  985.46   237.1  976.62     253  973.77   279.6  975.36
   295.5  972.86   300.8  972.55     316  972.93   327.3  977.03   357.7  979.24
   385.8  990.88   400.2  999.84   412.4 1003.63   433.6 1024.73   444.2 1039.91
   449.5 1045.74   471.9 1056.09   486.7 1066.58   527.9 1082.27   612.5 1135.62
#Mann= 3 ,-1,0
       0      .1       0   295.5    .045       0     316      .1       0
Bank Sta=295.5,316
XS Rating Curve= 0 ,0
Exp/Cntr(USF)=0,0
Exp/Cntr=0.3,0.1

Type RM Length L Ch R = 1 ,14003   ,506.1,501.3,488.8
XS GIS Cut Line= 6
1663547.60649967434272.1826065931663803.71425517434280.716710255
1663903.74653542434281.4227455851663978.90878667 434277.79709667
1664066.59955618434273.1924470961664161.87134726434280.545450762
#Sta/Elev= 30
       0 1019.42     4.5 1018.42      25 1009.03    52.5 1002.49    95.4  986.96
   104.6  982.68   124.4  983.46   200.6   978.4   244.6  976.88   280.7  973.82
  287.82969.6914   292.7  968.81   312.1  969.73   348.7  971.65   356.7  976.35
   372.7  982.99   376.7  985.86   404.7 1011.75   428.7 1032.54   452.8 1047.36
   480.8 1056.71   488.8 1060.44   508.8 1072.78   512.9 1074.46   524.9 1077.43
   540.9 1083.45   549.9 1085.73   565.2  1091.4     577 1097.06   614.9 1107.67
#Mann= 3 ,-1,0
       0      .1       0  287.82    .045       0   312.1      .1       0
Bank Sta=287.82,312.1
XS Rating Curve= 0 ,0
Exp/Cntr(USF)=0,0
Exp/Cntr=0.3,0.1

Type RM Length L Ch R = 1 ,13502   ,493.1,501.5,512.9
XS GIS Cut Line= 6
1663644.72244717434993.9354281721663809.92356034434797.806555346
1663871.49725609434719.0111092631663936.81536692434677.064670846
1664022.58389618434633.6710568371664123.33960018434595.574348256
#Sta/Elev= 30
       0 1160.79    43.1 1131.77    59.6 1118.57    70.1 1112.64    91.1 1095.92
      97 1088.86   101.6 1085.17   117.3 1080.25   139.6 1069.97     151 1056.66
   159.5 1051.55   166.1  1045.7   196.4 1010.45   209.8  999.37   234.8  983.99
   247.3   978.3     273  975.17   298.8  966.46   308.8  965.67   318.5   966.5
   355.8  971.18   383.2  970.11   414.2  971.03   446.7  975.02   478.1  976.22
   497.3  979.29   557.5 1009.62   578.6 1024.31   617.3 1044.79   637.9 1052.83
#Mann= 3 ,-1,0
       0      .1       0   298.8    .045       0   318.5      .1       0
Bank Sta=298.8,318.5
XS Rating Curve= 0 ,0
Exp/Cntr(USF)=0,0
Exp/Cntr=0.3,0.1

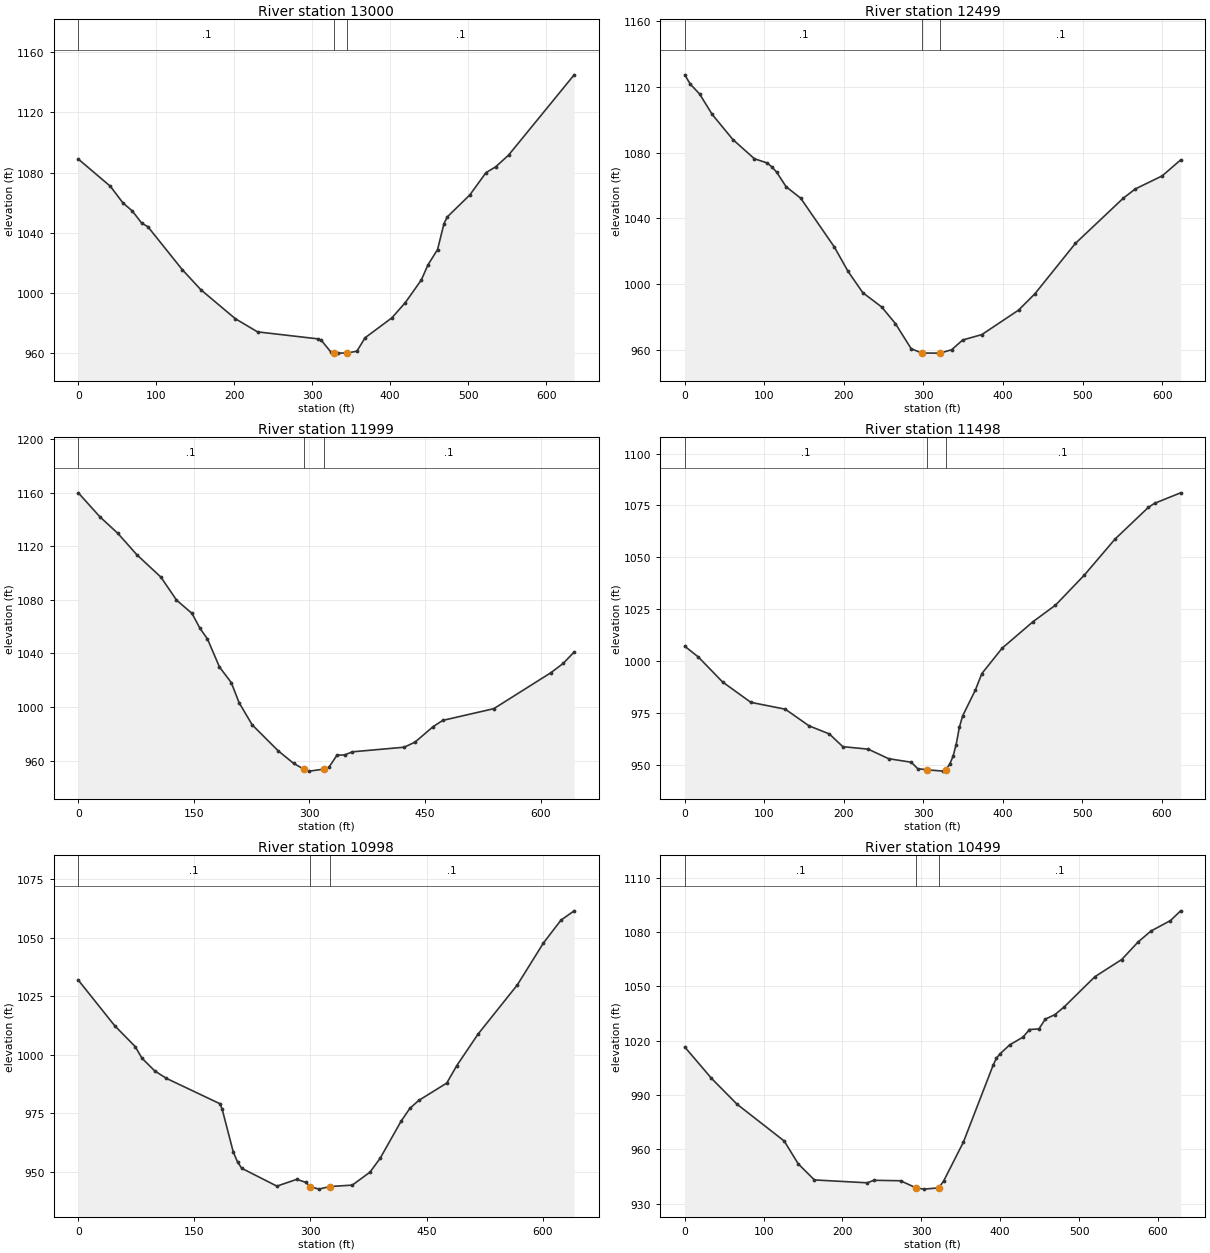
Type RM Length L Ch R = 1 ,13000   ,496.3,500.9,505.3
XS GIS Cut Line= 6
1663770.92888768435128.152679428 1663880.7984186435124.367582008
1663975.02067108435127.2993346751664049.00739975435142.286181346
1664145.75523776 435167.581406341664393.56707808435232.798139423
#Sta/Elev= 30
       0 1089.05    41.2 1070.93    57.2 1059.96    69.2 1054.62    81.2 1046.57
    89.2 1044.14   133.3 1015.64   157.3 1002.21   201.3  983.07   229.8  974.31
   307.7  969.64   311.8  968.58   324.2  960.71   328.4   960.3   332.5  960.19
   344.9  960.29   357.3  961.48   367.7  970.37   402.1  983.61   419.4  993.76
     440 1008.88   448.3 1018.72   460.7 1028.97     469 1046.27   473.1 1050.61
   502.1 1065.25   522.8 1080.04   535.2 1083.91   551.7 1091.63   635.9 1145.01
#Mann= 3 ,-1,0
       0      .1       0   328.4    .045       0   344.9      .1       0
Bank Sta=328.4,344.9
XS Rating Curve= 0 ,0
Exp/Cntr(USF)=0,0
Exp/Cntr=0.3,0.1

Type RM Length L Ch R = 1 ,12499   ,515.9,500,479.9
XS GIS Cut Line= 6
1663600.39412376435306.5355247561663770.22744551435499.084024176
1663840.93891826435569.7938565021663891.09597017435625.701225013
  1663944.819616435695.3132905071664031.57403567435751.736405998
#Sta/Elev= 30
       0 1127.44     6.9 1121.76    18.6 1115.78    34.5 1103.27    60.5 1087.97
    87.5 1076.29   103.2 1073.77   109.2 1071.47   115.3 1068.21   127.4 1059.21
   145.7 1052.24     188 1022.48   205.3 1007.57   223.8  994.63   247.6  985.88
   264.8  975.77   284.6  960.47     298 957.862   318.5  957.79   321.3  957.85
   335.5  959.87   349.3  965.79   373.5  969.11   419.6  984.02   440.1  993.96
     491 1024.68   551.4 1052.33   566.4 1057.89   600.1 1065.83   623.3 1075.55
#Mann= 3 ,-1,0
       0      .1       0     298    .045       0   321.3      .1       0
Bank Sta=298,321.3
XS Rating Curve= 0 ,0
Exp/Cntr(USF)=0,0
Exp/Cntr=0.3,0.1

Type RM Length L Ch R = 1 ,11999   ,494.1,501.1,506
XS GIS Cut Line= 6
1663459.60765992436163.2349268351663661.69419801436005.675202593
1663740.55690117435944.1877927481663803.23131651435902.596996665
1663885.63338268435859.710271418  1664001.980919435833.935060501
#Sta/Elev= 30
       0 1160.12    27.9 1142.24    51.4 1129.77    75.9 1113.86   107.2 1097.09
   127.4 1079.95   147.5 1069.98   157.9 1058.79   167.6 1050.88   183.2 1029.89
   198.5 1018.25   208.6  1003.3   225.6  986.69   259.3  967.29   279.6  957.77
     293  953.44   299.9  952.06   318.6  953.55   325.3  954.99   335.7  964.01
   345.5  964.14   355.7   966.5   422.9  969.94     437  973.76   460.3  985.25
     473     990   539.2  998.75     613 1025.53   629.3 1032.59   643.5 1041.16
#Mann= 3 ,-1,0
       0      .1       0     293    .045       0   318.6      .1       0
Bank Sta=293,318.6
XS Rating Curve= 0 ,0
Exp/Cntr(USF)=0,0
Exp/Cntr=0.3,0.1

Type RM Length L Ch R = 1 ,11498   ,512.3,500.2,491.1
XS GIS Cut Line= 6
1663749.26292051436420.2196490911663840.27586184436376.442833751
1663925.37378876436344.8739992531663998.82836625436327.026265919
1664097.94726251436313.6086418331664352.55830184436284.674644589
#Sta/Elev= 30
       0 1007.08    16.9 1001.96    47.6  989.84    83.1  980.04   126.4  976.74
   156.3  968.71   181.9  964.79   198.7  958.68   230.7  957.47   256.3  952.88
   284.8  951.17   292.9  948.08     305   947.5   325.2  946.88  328.35947.4894
   333.2  950.26   337.3  953.95   341.3  959.71   345.3  967.98   349.4  973.48
   365.5  986.02   373.6  993.92   399.2 1006.19     438 1018.95   466.2  1026.9
   502.4 1041.36   541.2  1058.8   582.9 1074.01   590.8    1076   623.6 1081.06
#Mann= 3 ,-1,0
       0      .1       0     305    .045       0  328.35      .1       0
Bank Sta=305,328.35
XS Rating Curve= 0 ,0
Exp/Cntr(USF)=0,0
Exp/Cntr=0.3,0.1

Type RM Length L Ch R = 1 ,10998   ,477.5,498.7,511.5
XS GIS Cut Line= 6
1663828.74209225 436978.858295591663919.31441768436939.511917591
1663996.33427675436892.2925238461664107.71233484436757.045419008
1664171.39166942436710.1734655051664353.53467783436636.114230424
#Sta/Elev= 30
       0 1031.86    46.9 1012.45    73.5 1003.51    82.2  998.57    98.7  993.13
   113.8  989.94   182.9  979.12   185.8  976.85   200.2  958.53   205.7  954.28
   211.1  951.56   256.6  943.94   282.3  946.84   293.8  945.56   299.5  943.77
   310.7  942.66   325.3  943.78     354  944.37   376.9  949.91   390.1  955.89
   416.9  971.57   428.4  977.15   439.8   980.5   476.1  987.94   488.8  995.26
   516.5 1008.83   567.2  1029.8     601 1047.72   623.6 1057.46   640.7 1061.45
#Mann= 3 ,-1,0
       0      .1       0   299.5    .045       0   325.3      .1       0
Bank Sta=299.5,325.3
XS Rating Curve= 0 ,0
Exp/Cntr(USF)=0,0
Exp/Cntr=0.3,0.1

Type RM Length L Ch R = 1 ,10499   ,516.8,495.3,479.8
XS GIS Cut Line= 6
1663838.75617984437191.7505863461663933.63787983437206.711842507
1664020.00712967 437227.544149921664258.24779493437304.833037332
1664347.87852117437307.4380190071664448.57746676437282.015825748
#Sta/Elev= 30
       0 1016.53    33.8  999.27    66.2     985   126.1  964.67   143.9  952.05
   164.4  943.19   231.4  941.61   239.9     943   273.6  942.74   293.4  938.81
     303  938.12     322   938.8   328.2   942.5   353.4  964.09   391.1 1006.51
   395.3 1010.41   399.5  1012.6   412.1 1017.74   428.9 1021.97   437.2 1026.18
   449.2 1026.53   457.2 1031.91   469.3 1034.37   481.3  1038.7     520 1055.28
   554.2 1064.82   574.8 1074.43   591.3 1080.54     616  1086.3   628.9 1091.68
#Mann= 3 ,-1,0
       0      .1       0   293.4    .045       0     322      .1       0
Bank Sta=293.4,322
XS Rating Curve= 0 ,0
Exp/Cntr(USF)=0,0
Exp/Cntr=0.3,0.1

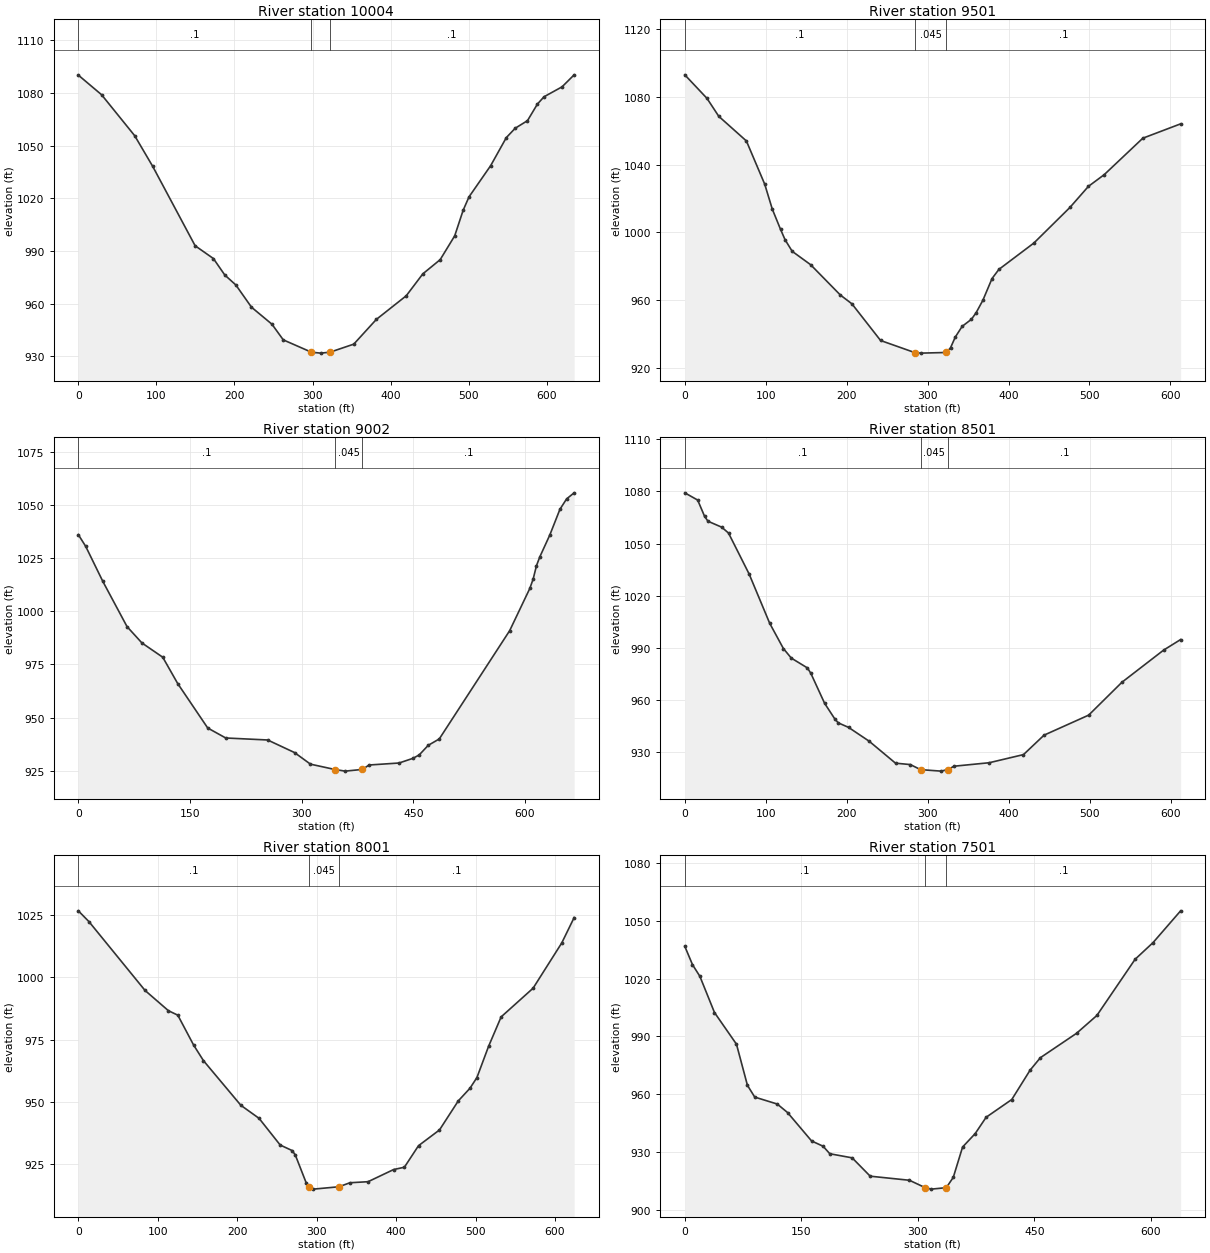
Type RM Length L Ch R = 1 ,10004   ,495.4,502.6,502.1
XS GIS Cut Line= 6
1664130.81235425437848.3073440941664243.24520026437693.416577756
1664284.25266418437626.602406919  1664351.724314437464.520710096
1664394.61661667437387.281691343 1664471.9465145437321.937661916
#Sta/Elev= 30
       0 1090.12    29.8 1078.95    72.2 1055.64    95.3 1038.17   149.6  993.02
     173  985.74   187.6  976.37   201.8  970.68   221.8  958.04     248  948.37
   262.5  939.46   298.6  932.43   310.5  931.91  322.34932.4382   352.8  937.02
   381.7  951.09     420  964.54   441.3  977.04   463.5  985.11   482.1  998.66
   492.9  1013.2   500.4 1020.83   528.2 1038.63   548.2 1054.56   559.6  1059.9
   575.3  1064.2     588 1073.62   596.5  1077.8   619.6 1083.46   635.1 1090.29
#Mann= 3 ,-1,0
       0      .1       0   298.6    .045       0  322.34      .1       0
Bank Sta=298.6,322.34
XS Rating Curve= 0 ,0
Exp/Cntr(USF)=0,0
Exp/Cntr=0.3,0.1

Type RM Length L Ch R = 1 ,9501    ,490.4,498.8,506.2
XS GIS Cut Line= 6
1664452.97509576438160.756850421 1664516.1573841438091.436779082
1664573.06278209438024.9651272591664685.78663801 437891.10548684
  1664734.609375437834.1689209191664853.50152567437697.332908511
#Sta/Elev= 30
       0 1092.99    27.4  1079.1      42 1068.48    76.1 1053.94    98.7 1028.47
   108.1  1013.7   118.3 1001.73   123.9   995.6   132.7  988.77   155.5  980.86
   192.2  962.96   206.5  957.76   241.9  936.12  284.08  928.99   291.6  928.66
     323  929.04   328.3  931.79   334.2  938.16   342.7  944.47   354.1  948.63
   359.9  952.49   368.3  959.89   379.6  972.71   388.1  978.11   431.3  993.67
   475.8 1014.66   498.7 1027.14   518.2 1034.04   565.9 1055.57   612.6 1064.04
#Mann= 3 ,-1,0
       0      .1       0  284.08    .045       0     323      .1       0
Bank Sta=284.08,323
XS Rating Curve= 0 ,0
Exp/Cntr(USF)=0,0
Exp/Cntr=0.3,0.1

Type RM Length L Ch R = 1 ,9002    ,487.6,501.2,516.8
XS GIS Cut Line= 6
1664602.70773593438324.9569813461664726.78163476438325.321810007
1664829.63871251 438338.825063841664911.39543876438334.683996007
 1665001.3847601438291.001340583 1665229.0434255   438173.377232
#Sta/Elev= 30
       0 1036.06     9.9 1030.56    32.9 1014.07    65.4  992.79    85.4   985.1
   113.4  978.37   133.5  965.97   173.8  945.06     198  940.36   254.3  939.42
   290.4   933.5   311.8  928.04   344.7  925.52   358.4  924.76   381.6  925.56
   390.5  927.64   430.8  928.58   449.2  930.75   457.8  932.36     470  936.91
   484.8   939.9   579.4  990.89   606.4 1010.73   610.9 1015.13   615.4 1021.49
   619.9 1025.64   633.4 1035.99   646.9 1048.02   655.9 1052.92     666 1055.76
#Mann= 3 ,-1,0
       0      .1       0   344.7    .045       0   381.6      .1       0
Bank Sta=344.7,381.6
XS Rating Curve= 0 ,0
Exp/Cntr(USF)=0,0
Exp/Cntr=0.3,0.1

Type RM Length L Ch R = 1 ,8501    ,497,500,502.2
XS GIS Cut Line= 6
1664441.10110375438620.0193833411664529.60945693438650.927458003
1664683.02450442438704.5011697561664848.24070942438762.195608169
   1664930.84914438791.041679084 1665020.1462055438819.690571919
#Sta/Elev= 30
       0 1079.17    15.9 1075.01    24.4 1065.71    28.6 1062.86    45.6 1059.43
      54 1056.06    79.5 1032.49   104.9 1004.18   121.8   989.7   131.5  984.23
   151.5  978.55   155.7  975.46   172.7  958.24   185.4  949.18   189.6  946.99
   202.3  944.39   227.7  936.47   260.3  923.83   278.6  923.03   291.3  920.11
   316.6  919.26   325.2  920.18   332.5  922.08     376  924.08   418.4  928.76
   443.8  939.93   498.9  951.43     540  970.32   591.5   988.8   612.5  994.87
#Mann= 3 ,-1,0
       0      .1       0   291.3    .045       0   325.2      .1       0
Bank Sta=291.3,325.2
XS Rating Curve= 0 ,0
Exp/Cntr(USF)=0,0
Exp/Cntr=0.3,0.1

Type RM Length L Ch R = 1 ,8001    ,519.2,500,468.7
XS GIS Cut Line= 6
 1664205.2820216438989.1383957561664429.28551058439113.583356842
1664516.70101817439162.1475641731664582.26322301439198.570063502
1664658.75125901439241.0653853421664763.58438267439251.046008423
#Sta/Elev= 30
       0 1026.85    13.4 1022.49      84  994.77   113.4  986.62   125.2  984.82
   145.1  972.79   157.5   966.5   204.6  948.51   227.5  943.26   254.1  932.51
   269.3  930.26   273.2  928.43   286.9  917.21   289.9  915.76   295.8  914.75
     328   915.7   341.9  917.32   364.7  917.74   396.8  922.63   410.4  923.57
   428.2  932.25   454.6  938.59   478.2  950.27   492.9  955.36   501.7  959.68
   516.4  972.29   532.2  984.13   572.4  995.68   608.5 1013.92   624.1 1024.15
#Mann= 3 ,-1,0
       0      .1       0   289.9    .045       0     328      .1       0
Bank Sta=289.9,328
XS Rating Curve= 0 ,0
Exp/Cntr(USF)=0,0
Exp/Cntr=0.3,0.1

Type RM Length L Ch R = 1 ,7501    ,477.8,500,519.5
XS GIS Cut Line= 6
1664335.67283693439750.6450748441664422.48729584439696.680615842
1664498.67447942439642.2561840121664551.43191984439586.622108921
1664689.46018709 439363.341387511664778.93901075439312.184009507
#Sta/Elev= 30
       0 1036.72     9.9  1027.2    19.4 1021.14    38.2 1002.33    66.5  985.88
    80.6  964.53      90   958.4     119  954.79   132.2  950.39   163.2   935.6
     178  932.87   186.6  928.97   215.4  926.84   238.6  917.31   289.1  915.19
   309.4  911.35   317.3  910.59  336.54911.3488   345.5  916.68   357.5  932.46
   373.7  939.43   387.8  947.92   420.8  957.14   444.3  972.34   457.6  978.86
   504.1  991.52   530.3 1000.79   579.5 1029.98   602.6 1038.65   638.1 1055.16
#Mann= 3 ,-1,0
       0      .1       0   309.4    .045       0  336.54      .1       0
Bank Sta=309.4,336.54
XS Rating Curve= 0 ,0
Exp/Cntr(USF)=0,0
Exp/Cntr=0.3,0.1

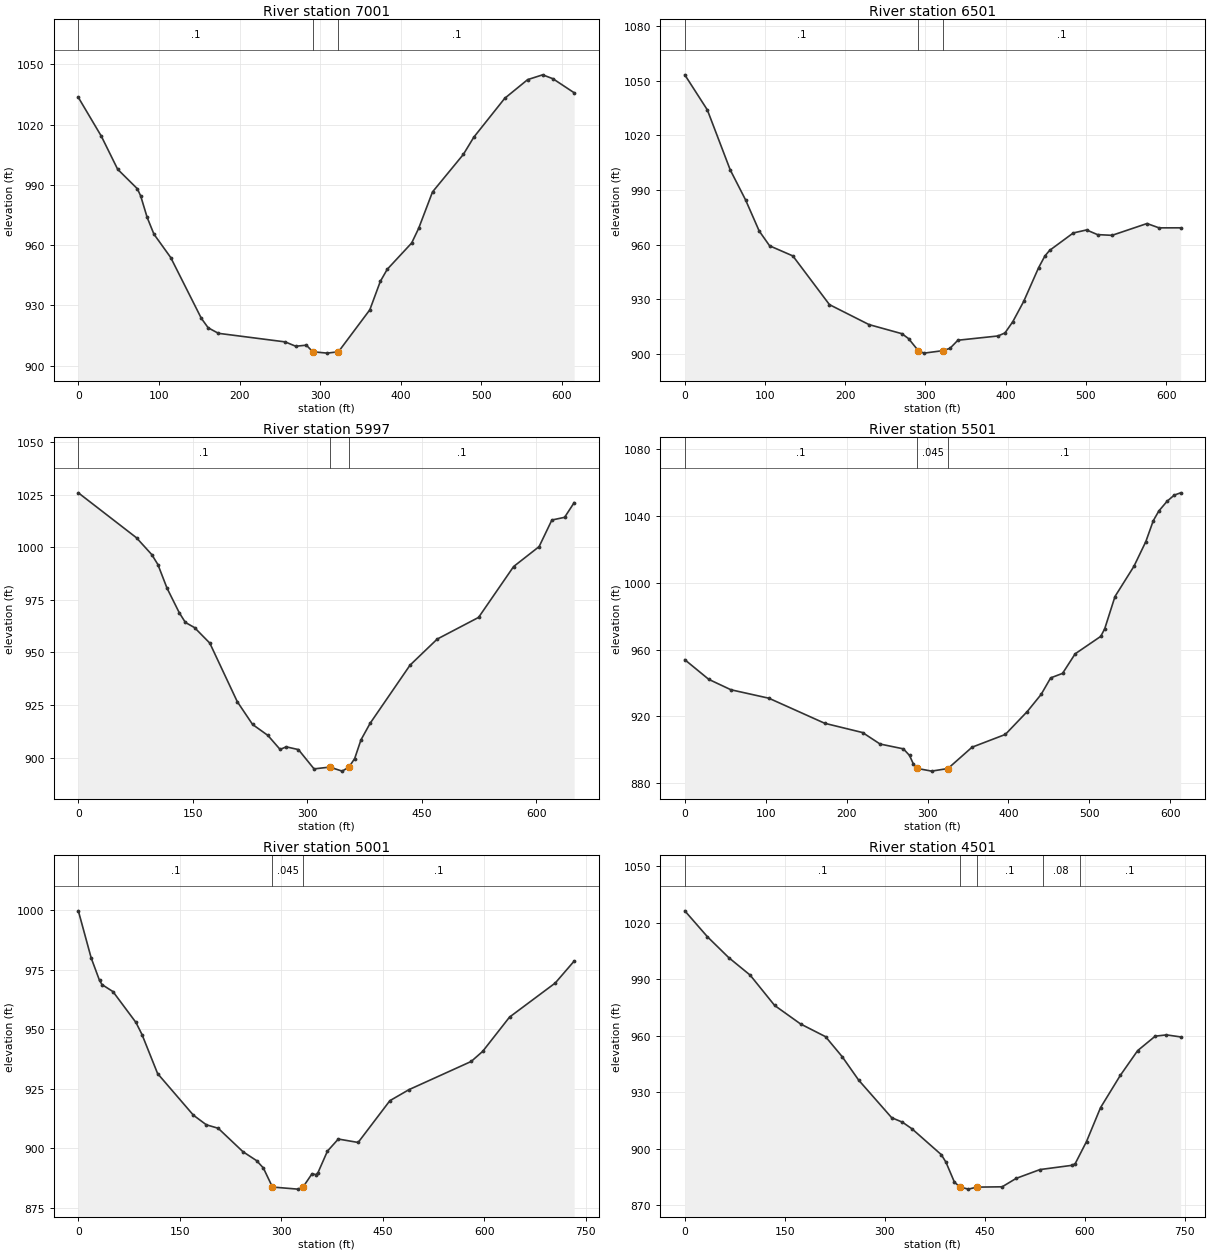
Type RM Length L Ch R = 1 ,7001    ,517,500,488.4
XS GIS Cut Line= 6
1664360.04352309439912.5364833331664454.14832176439929.176870003
1664537.23411359439957.6646739241664697.15144467440028.738022596
1664766.51022984440057.3475454151664936.84781568440120.590857252
#Sta/Elev= 30
       0 1033.49    28.5  1014.2    48.8  997.71    73.2  988.02    77.3  984.49
    85.4  973.74    93.8  965.41   114.6  953.78   152.6  923.51   161.1  918.79
   173.8  916.05   256.6  911.78   269.7  909.62   282.9  910.15   290.8  906.87
   308.7  906.19   322.7906.8737   361.6  927.75   374.6  941.88   383.2  947.91
   413.5     961   422.2  968.31   439.4  986.45   477.6  1005.1   490.6 1013.68
     529 1033.05   557.4 1042.34     576 1044.73   588.8 1042.78   615.1  1035.8
#Mann= 3 ,-1,0
       0      .1       0   290.8    .045       0   322.7      .1       0
Bank Sta=290.8,322.7
XS Rating Curve= 0 ,0
Exp/Cntr(USF)=0,0
Exp/Cntr=0.3,0.1

Type RM Length L Ch R = 1 ,6501    ,488.8,503.9,510
XS GIS Cut Line= 6
1664368.61240359440578.323865667 1664463.5630011440559.083746672
 1664550.1313975440535.6868118351664616.29432292440500.304664761
1664844.53730476440370.6441629231664928.80813359440329.233812675
#Sta/Elev= 30
       0 1053.14    28.1 1033.91    56.6 1001.05    75.8  984.52    92.7  967.54
   105.7   959.4   134.7  953.85   180.3  927.15   229.6  916.21   270.6  911.21
   278.9  908.52  291.03901.9279   298.2  900.56   321.3  901.89   330.5  903.18
   340.4  907.63   390.4  909.97   399.1  911.64   408.8  917.78   422.4  928.91
     441  947.42   448.9  953.87   454.8  956.92   484.2  966.44   500.7  968.09
   514.4  965.54   532.5  965.14   576.1  971.61   591.1  969.24     618  969.26
#Mann= 3 ,-1,0
       0      .1       0  291.03    .045       0   321.3      .1       0
Bank Sta=291.03,321.3
XS Rating Curve= 0 ,0
Exp/Cntr(USF)=0,0
Exp/Cntr=0.3,0.1

Type RM Length L Ch R = 1 ,5997    ,490.3,496.1,498.6
XS GIS Cut Line= 6
1664467.94127317440915.8002248411664570.51357459440912.395376012
1664668.43923175440912.0558097511664755.19496375440916.129620507
  1664858.660308440938.6180925821665104.10371476441012.250163168
#Sta/Elev= 30
       0 1025.82    76.2 1004.45    96.2  996.46   104.2  991.75   116.2  980.49
   132.2  968.84   140.2  964.22   152.2  961.76   172.2  954.39   208.2  926.55
   228.3   915.7   248.3  910.51   264.3  903.84   272.3  905.08   288.3  903.77
   308.8  894.59   329.3  895.45   345.6  893.53  354.56895.4868     362  899.51
   370.2  908.36   382.2  916.25   434.5   943.9   470.1   956.3   524.3   966.6
   570.2  990.78   603.6 1000.26   620.3 1012.89     637 1014.18   649.5 1021.16
#Mann= 3 ,-1,0
       0      .1       0   329.3    .045       0  354.56      .1       0
Bank Sta=329.3,354.56
XS Rating Curve= 0 ,0
Exp/Cntr(USF)=0,0
Exp/Cntr=0.3,0.1

Type RM Length L Ch R = 1 ,5501    ,521.6,500.4,464.4
XS GIS Cut Line= 6
1664322.78900443441210.9115112571664402.99848968441259.669943929
 1664479.4409221 441302.259425671664699.26331709441421.331037924
1664776.14702159441463.1062168331664857.34535001 441510.03886576
#Sta/Elev= 30
       0  953.92    29.6  942.17      57  935.93   103.9  930.87     173  915.85
   219.7  910.32   241.3  903.45   270.1  900.56   277.7  896.62   282.2  891.78
   286.9  888.88     305  887.23   325.2  888.79     355  901.56   396.1  909.19
   423.2  922.91   440.3  933.13   452.1  943.04   466.8  945.74   482.4  957.46
     514  967.89   518.9  972.44   531.6  991.75     555 1009.82   569.7 1024.62
   578.9 1037.11   585.7  1042.9     596 1048.78   604.8 1052.43   612.7 1053.81
#Mann= 3 ,-1,0
       0      .1       0   286.9    .045       0   325.2      .1       0
Bank Sta=286.9,325.2
XS Rating Curve= 0 ,0
Exp/Cntr(USF)=0,0
Exp/Cntr=0.3,0.1

Type RM Length L Ch R = 1 ,5001    ,509.9,500,492.4
XS GIS Cut Line= 6
1664125.95868942441914.6151563381664317.06001326441743.897978082
 1664392.1671465441677.8708791731664498.10886376441670.371550336
1664628.91207984441662.156999841  1664766.191989441638.208884999
#Sta/Elev= 30
       0  999.66      19  979.87    31.3  970.45    35.1  968.67    51.2  965.75
    85.2  952.78    94.1  947.73   117.2  931.32   170.1  913.86   189.2  909.83
   206.7  908.38   243.3  898.54   263.6  894.76   273.5   891.7   286.9   883.7
   324.2  882.82   331.7  883.51   345.5   889.3   351.5   888.9   354.3  889.78
   368.2  898.77   384.3  903.85   413.6  902.41   460.5  919.95   488.7  924.58
   580.7  936.42   597.7  940.66   637.4  955.05   704.9  969.34   732.9  978.56
#Mann= 3 ,-1,0
       0      .1       0   286.9    .045       0   331.7      .1       0
Bank Sta=286.9,331.7
XS Rating Curve= 0 ,0
Exp/Cntr(USF)=0,0
Exp/Cntr=0.3,0.1

Type RM Length L Ch R = 1 ,4501    ,463.7,502.4,528.6
XS GIS Cut Line= 6
1664402.12742843442131.8699711711664581.04931468442137.017598674
1664707.84761751442102.4428646711664747.95252417442036.762221754
1664830.96285684441787.7328641711664867.21737751441700.996817172
#Sta/Elev= 30
       0  1026.4      34 1012.59      66 1001.49      98  992.23   134.8  976.08
   173.7  966.24   211.2  959.47   236.1  948.86   260.9  936.36   310.4  916.39
   326.6  913.99   340.8   910.5   384.8  896.75   391.8  892.75   404.5  882.14
   412.8  879.53   425.4  878.41   438.2  879.47   476.2  879.65   497.2  884.13
   532.9  888.81   581.6   891.1   585.8  892.01   602.7  903.72   623.7  921.71
   653.3  938.84   679.4  952.06   705.8  959.75   722.7  960.42   743.9  959.35
#Mann= 5 ,-1,0
       0      .1       0   412.8    .045       0   438.2      .1       0
  537.38     .08       0  592.38      .1       0
Bank Sta=412.8,438.2
XS Rating Curve= 0 ,0
Exp/Cntr(USF)=0,0
Exp/Cntr=0.3,0.1