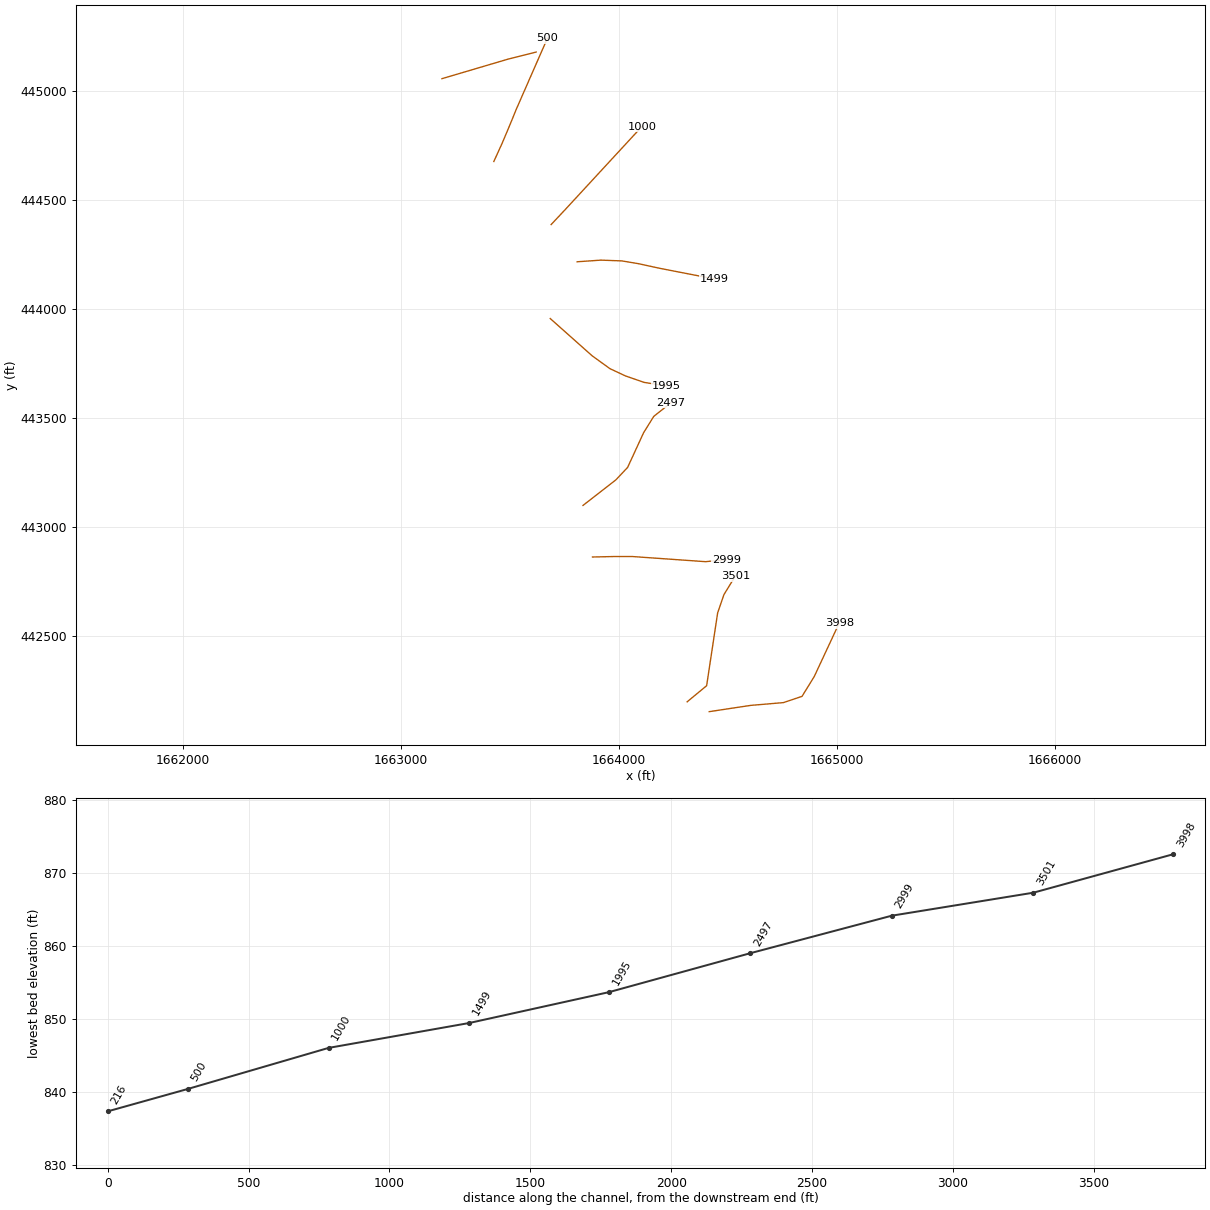
HEC-RAS study ROCKYRN.prj: ROCKYRN

--- ROCKYRN.g01 (geometry) --- (continued)

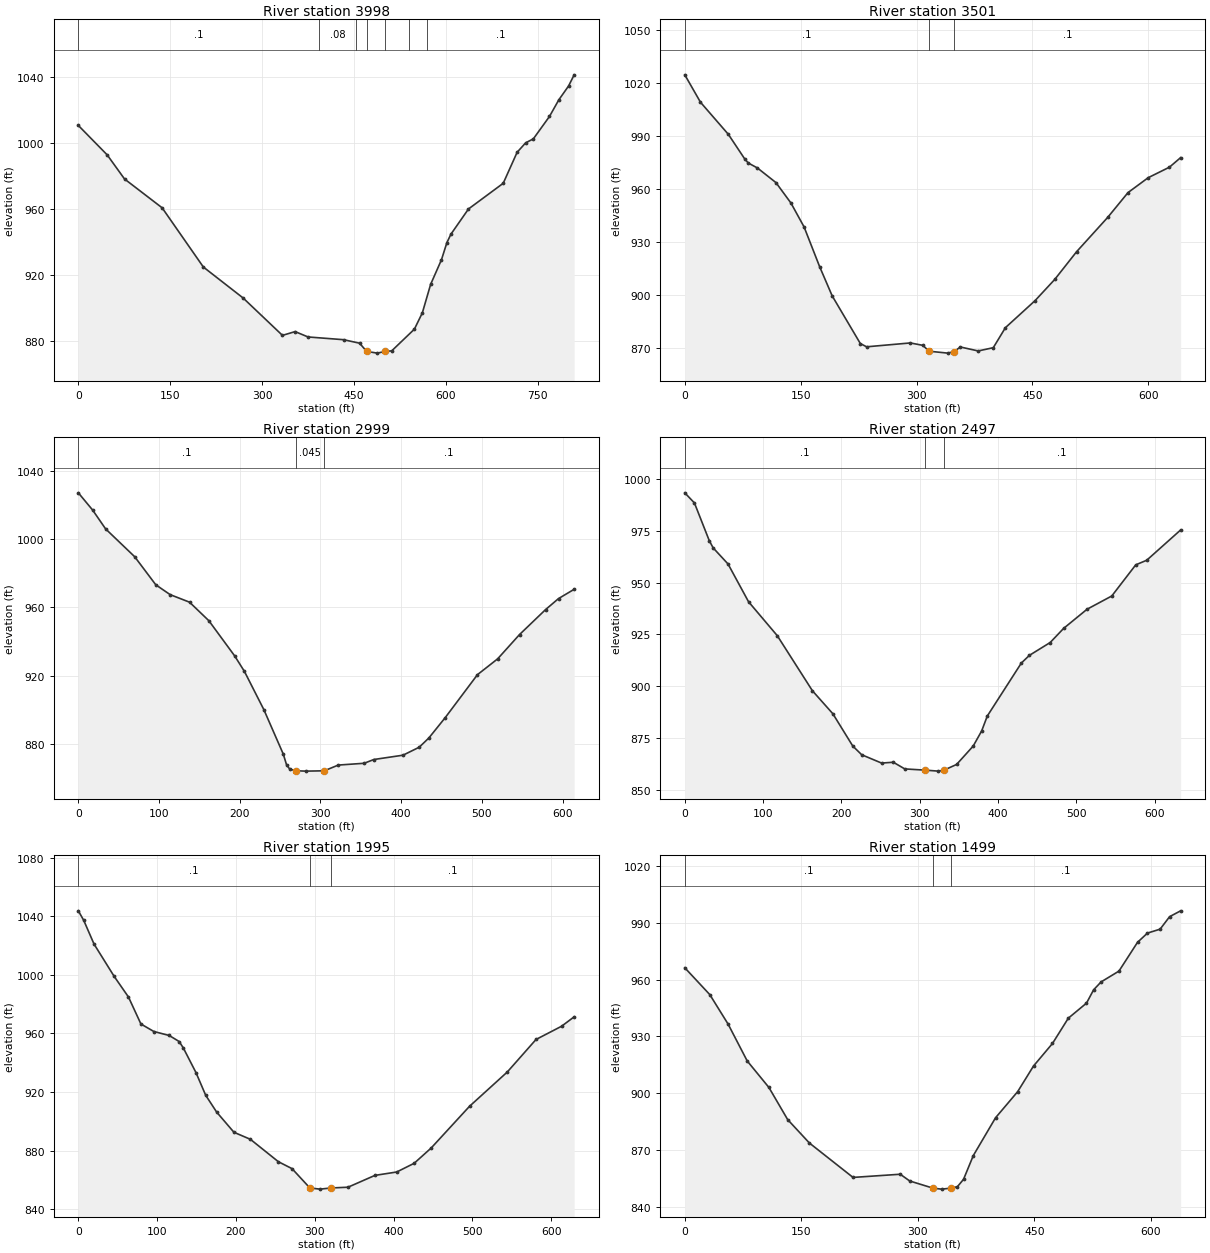
Type RM Length L Ch R = 1 ,3998    ,491.5,497.2,502.2
XS GIS Cut Line= 6
1664413.52635576442155.4775355011664603.84716934442184.233055428
1664753.44332685442196.8737781791664839.14427093442225.624048755
1664895.10347658442316.3581192491665009.24465251442560.790701255
#Sta/Elev= 30
       0 1010.74    47.1  992.87    75.4  978.25   136.8  960.75   204.1  924.81
     269  906.02   333.2  883.34   353.9  885.62     375  882.37     433  880.71
   459.1  878.59   470.7   873.6   488.1  872.56   500.3  873.55   511.6  873.94
   548.6  887.11   561.6  897.03   575.1  914.28   592.8  929.24   601.6  939.58
   608.2  944.73   636.9  960.05   693.6  975.64   716.3  994.45   730.2 1000.18
   742.8 1002.61   769.1 1016.19   784.3 1026.25   800.3 1034.69   809.4 1041.46
#Mann= 7 ,-1,0
       0      .1       0  392.61     .08       0  453.01      .1       0
   470.7    .045       0   500.3      .1       0  539.61     .08       0
  569.61      .1       0
Bank Sta=470.7,500.3
XS Rating Curve= 0 ,0
Exp/Cntr(USF)=0,0
Exp/Cntr=0.3,0.1

Type RM Length L Ch R = 1 ,3501    ,526,502.3,476.3
XS GIS Cut Line= 6
1664312.46651851442200.5745581691664401.72782293442274.427100763
1664414.81375475442360.9426757541664452.20409992442608.131157756
1664481.16204725442692.2461470071664533.45623401442776.917237505
#Sta/Elev= 30
       0 1024.44    20.3 1008.97    56.4  990.82    77.4  977.05    82.1  974.67
    94.1  971.81     118  963.58   137.4  952.04   154.4  938.54   174.6  916.03
   190.8  899.59   227.2   872.7   235.3  870.85   291.9  873.03   308.1  871.68
   316.2  868.36   340.5  867.28   348.6  868.17   356.7  870.74   379.8  868.51
   399.3  870.35     415  881.65   453.4  896.93   478.8  908.87   507.1  924.53
   547.4  943.93   573.7  957.94   599.9  966.37   627.3  972.28   641.8  977.68
#Mann= 3 ,-1,0
       0      .1       0   316.2    .045       0   348.6      .1       0
Bank Sta=316.2,348.6
XS Rating Curve= 0 ,0
Exp/Cntr(USF)=0,0
Exp/Cntr=0.3,0.1

Type RM Length L Ch R = 1 ,2999    ,481,502.1,514.4
XS GIS Cut Line= 6
1663878.35255735442864.2175878441663972.62041342442866.329788342
1664060.40567093442866.4462579191664135.22146617442861.194299921
1664397.07756975442842.8167120071664491.41366717442852.202520013
#Sta/Elev= 30
       0 1027.14    17.8    1017    33.8 1006.02    69.8  989.73      96  973.26
   113.8   967.5   137.8  963.09   161.8   952.2   193.8  931.57   205.8  922.55
   229.9  900.13     254  874.06     258  867.86     262  865.29   269.8  864.33
     282  864.13   304.8  864.32   322.1  867.68   354.2  868.73   366.2  870.94
   402.3  873.46   422.4  878.13   434.4  883.57   454.5  895.38   494.6  920.64
   519.6   929.9   546.7  944.12   578.9  958.71     595  965.19   614.4  970.64
#Mann= 3 ,-1,0
       0      .1       0   269.8    .045       0   304.8      .1       0
Bank Sta=269.8,304.8
XS Rating Curve= 0 ,0
Exp/Cntr(USF)=0,0
Exp/Cntr=0.3,0.1

Type RM Length L Ch R = 1 ,2497    ,523.9,501.9,478.8
XS GIS Cut Line= 6
1663834.84903543443100.661668763   1663985.41796443217.607629091
 1664039.5379305443274.9585642521664112.86422743443434.161657929
1664159.42187709443508.8731226771664238.08674601 443571.00127925
#Sta/Elev= 30
       0  993.32    12.3  988.43    31.2  970.28    36.2  966.75    55.2  958.98
    81.4  940.75   118.1  924.37     163  897.77   189.1  886.68   214.5  871.11
   225.9   866.9   251.3  862.88   266.3  863.28   280.9  860.06   306.3  859.48
   323.8  858.99   330.4  859.36   347.1  862.21   368.3  871.09   379.1  878.38
   386.3  885.58   429.8  911.16   440.1  914.88   466.6  921.06   483.8  927.89
   513.7  937.13   545.3  943.53   575.9  958.56   589.9  960.78   633.2  975.39
#Mann= 3 ,-1,0
       0      .1       0   306.3    .045       0   330.4      .1       0
Bank Sta=306.3,330.4
XS Rating Curve= 0 ,0
Exp/Cntr(USF)=0,0
Exp/Cntr=0.3,0.1

Type RM Length L Ch R = 1 ,1995    ,490.5,496.1,500.7
XS GIS Cut Line= 6
1663684.54848301443957.1323967581663876.06876926443786.885361925
1663957.91539034443727.6692730041664028.83716451443694.384562671
1664115.10503659443664.4141501781664215.92832576443648.771464929
#Sta/Elev= 30
       0 1043.68     6.9 1037.12    19.9    1021    45.4  998.97    63.6  984.83
    79.4  966.41    95.8  961.28   115.3  958.56   127.9  954.44   133.2  950.05
   149.3  933.15   161.6  917.71   175.5  906.23   197.4  892.47   218.3  887.66
   253.8  872.36   271.1  867.64  293.79854.4172   306.7  853.65   320.5  854.43
   342.1  854.96   376.3  863.04   403.9  865.34     426  871.28   447.6  881.72
   496.3  910.23   544.2  933.64   580.6  955.83     613  964.86     629   971.3
#Mann= 3 ,-1,0
       0      .1       0  293.79    .045       0   320.5      .1       0
Bank Sta=293.79,320.5
XS Rating Curve= 0 ,0
Exp/Cntr(USF)=0,0
Exp/Cntr=0.3,0.1

Type RM Length L Ch R = 1 ,1499    ,487.2,498.9,511.9
XS GIS Cut Line= 6
1663808.02855101444217.2089763431663916.91055109444224.746690929
1664012.61836493444221.2663829181664088.76978743444208.545607835
1664186.51270217   444187.3022121664438.07125418 444138.49259834
#Sta/Elev= 30
       0  966.28    32.2   952.1    55.7  936.58    80.3  917.12   108.3  903.09
   132.4  886.16   160.4  873.77   216.6   855.6   277.4  857.28   289.6  853.72
   319.8  849.91   330.6  849.42   342.9  849.93     351  850.72   358.9   854.6
   371.5  867.16   400.1  887.09   428.6  900.89     449  914.42   473.4  926.31
   493.8  939.66   517.2  947.61   526.4  954.65     536  958.81     559  964.52
   582.9  979.71   595.7  984.59     612  986.66   624.2  993.25   638.4  996.34
#Mann= 3 ,-1,0
       0      .1       0   319.8    .045       0   342.9      .1       0
Bank Sta=319.8,342.9
XS Rating Curve= 0 ,0
Exp/Cntr(USF)=0,0
Exp/Cntr=0.3,0.1

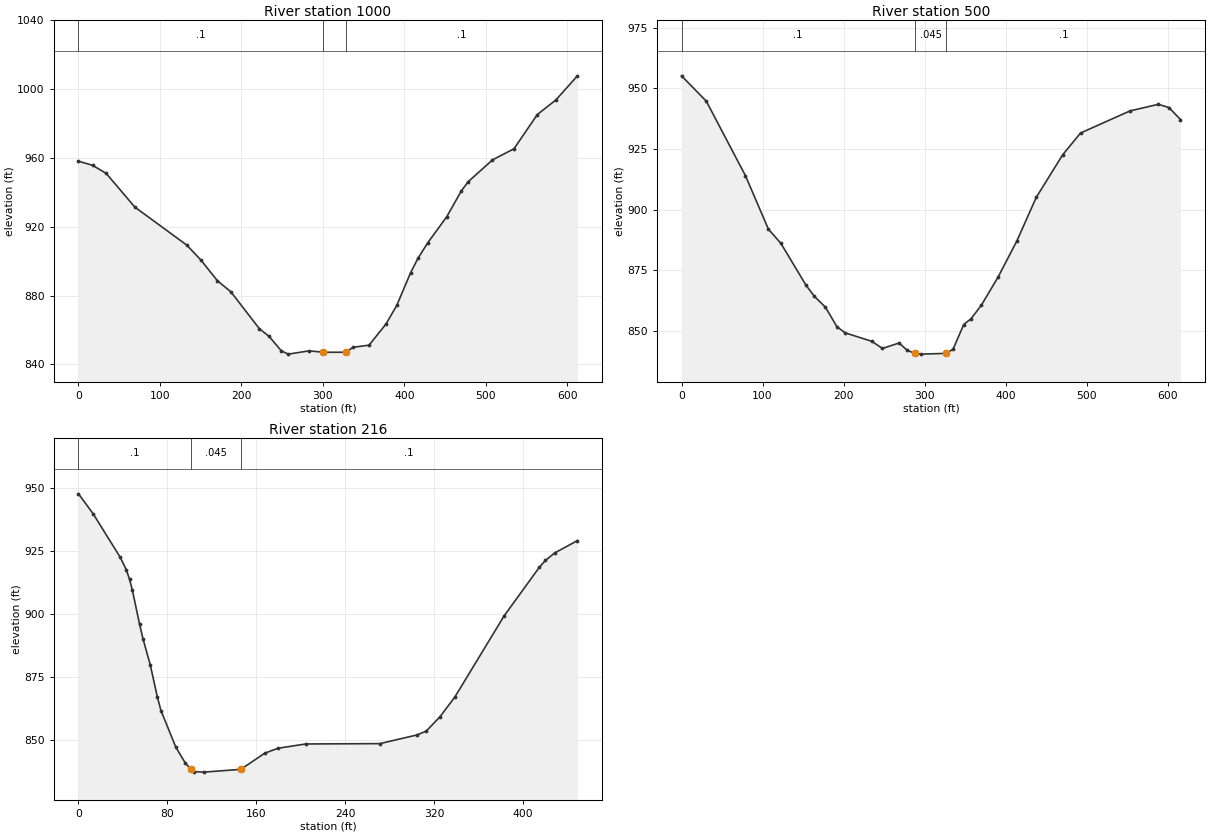
Type RM Length L Ch R = 1 ,1000    ,491.5,500,505
XS GIS Cut Line= 6
1663688.78371076 444387.763753341663752.98305742444456.095309585
1663812.39566825444520.3487900051663981.96619526444704.049210012
1664041.36273001444768.2846458411664105.00597543444837.113904506
#Sta/Elev= 30
       0  958.12    17.5  955.67      34  951.04    69.1  931.47   133.1  909.29
   150.1  900.76   170.6  888.63     187  882.26   222.1  860.74   233.9  856.35
   249.1  847.87   257.5  846.01   283.1  847.91  300.66847.1069   328.4  847.09
   336.9  849.96   356.7  851.22   377.5  863.51   390.7   874.3   407.7   893.3
   416.7  901.64   428.5  910.54   452.1  925.85   469.9  940.78   478.4   946.2
   508.2  958.86   534.6  965.34   563.3  985.23     586  993.68   612.5 1007.71
#Mann= 3 ,-1,0
       0      .1       0  300.66    .045       0   328.4      .1       0
Bank Sta=300.66,328.4
XS Rating Curve= 0 ,0
Exp/Cntr(USF)=0,0
Exp/Cntr=0.3,0.1

Type RM Length L Ch R = 1 ,500     ,299.6,284.3,262.7
XS GIS Cut Line= 6
1663425.93548317444676.7356163411663465.69360575444763.981504843
1663500.20009843444845.9091625061663528.57241701444915.361779511
1663568.73834717445006.9409926681663671.66235392445241.612111256
#Sta/Elev= 30
       0  955.21    30.6  944.75    78.9  914.03   107.3  891.93   122.6  886.13
   153.6  868.88   163.9  864.26   177.6  859.79   191.9  851.67   202.1  849.15
   235.1  845.64     248  842.72   268.6  844.97   278.6  841.97   287.7  840.73
     296  840.38   327.1  840.69   335.3  842.44   348.4  852.59   357.5  854.99
   370.3  860.63   390.9  872.21     414  887.07   437.9  905.01   470.7  922.69
   492.6   931.6   553.7  940.73   588.7  943.46   601.8  942.11     616  937.19
#Mann= 3 ,-1,0
       0      .1       0   287.7    .045       0   327.1      .1       0
Bank Sta=287.7,327.1
XS Rating Curve= 0 ,0
Exp/Cntr(USF)=0,0
Exp/Cntr=0.3,0.1

Type RM Length L Ch R = 1 ,216     ,,,
XS GIS Cut Line= 3
1663188.08297358445056.3505195331663489.47779611445145.426722143
1663620.04154514445178.372714889
#Sta/Elev= 30
       0  947.81    13.1  939.96    37.6  922.58      43  917.66    45.9   913.9
    48.5  909.51    54.9  896.13    58.1  890.13    64.6  879.88      71  867.04
    74.2  861.76    87.6  847.18      96  841.01  101.22838.3882   104.3  837.52
   112.7  837.31     146  838.41   167.6  844.83   179.4  846.78   204.4  848.49
   271.2  848.63   304.5  852.07   312.9   853.6   325.3  859.33   338.8  867.26
     383  899.39   414.5  918.57   420.1  921.38   428.4  924.33   448.9  929.23
#Mann= 3 ,-1,0
       0      .1       0  101.22    .045       0     146      .1       0
Bank Sta=101.22,146
XS Rating Curve= 0 ,0
Exp/Cntr(USF)=0,0
Exp/Cntr=0.3,0.1
LCMann Table=0

Chan Stop Cuts=-1
Use User Specified Reach Order=0
Composite Channel Slope=5